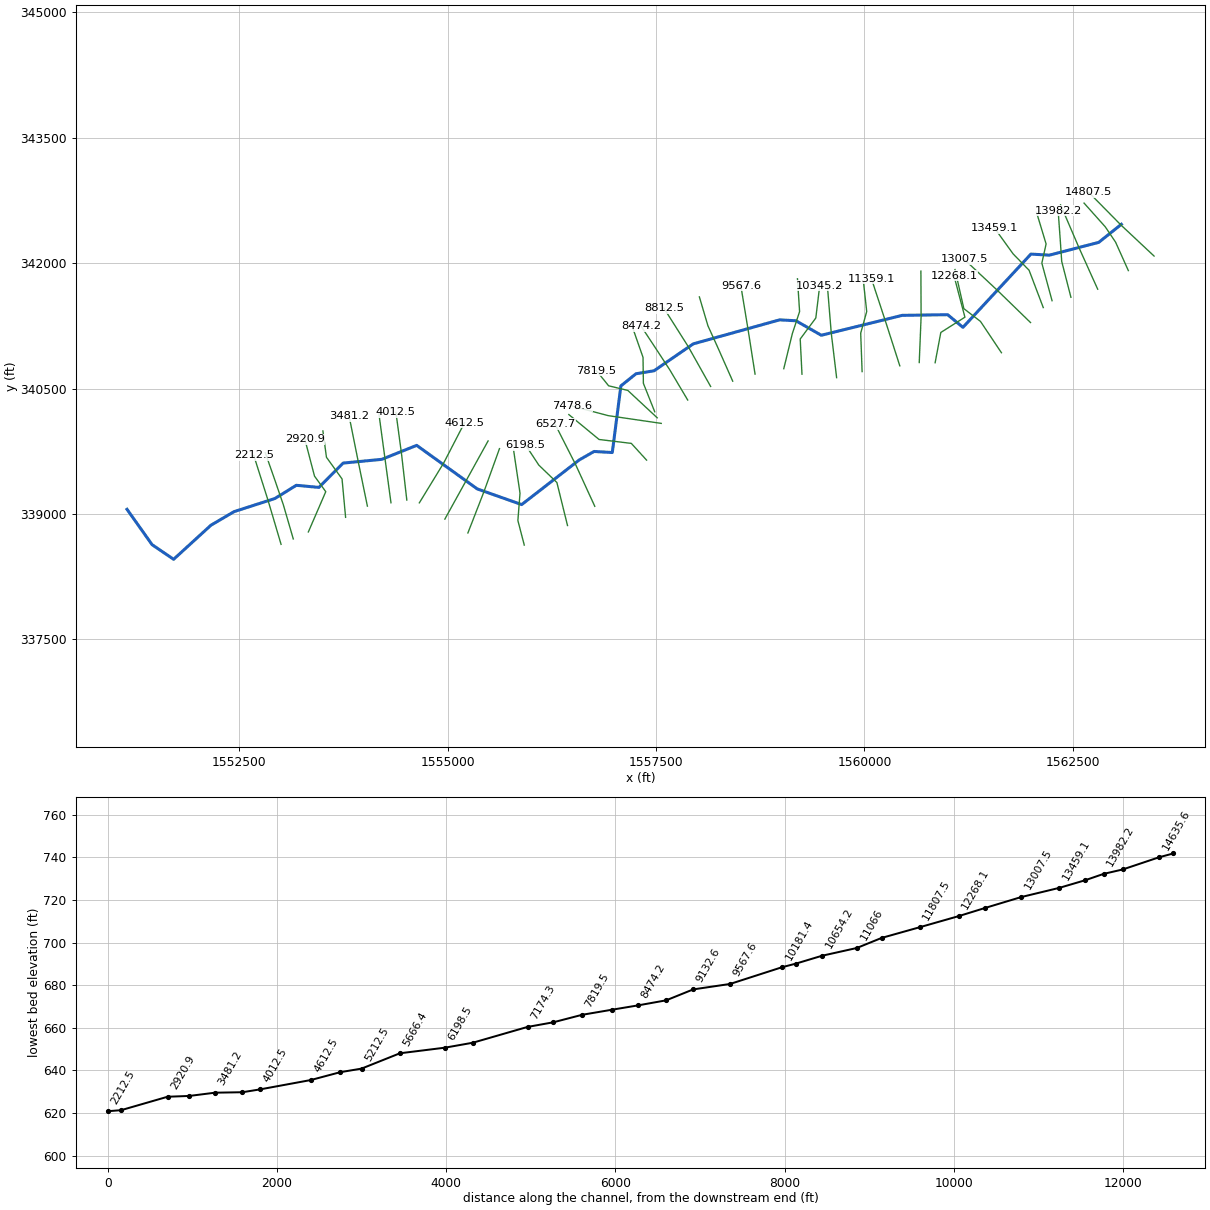
--- RFBULLCR.prj (project) ---

Proj Title=RFBULLCR
Current Plan=p01
Default Exp/Contr=0,0
English Units
Geom File=g01
Flow File=f01
Plan File=p01
BEGIN DESCRIPTION:
END DESCRIPTION:
DSS Export Rating Curves= 0
DSS Export Rating Curve Sorted= 0
DSS Export Volume Flow Curves= 0
DXF OffsetX= 0
DXF OffsetY= 0
DXF ScaleX= 0
DXF ScaleY= 0

--- RFBULLCR.p01 (plan) ---

Plan Title=Floodplain
Program Version=4.00
Geom File=g01
Flow File=f01
K Sum by GR=0
Std Step Tol=0.01
Critical Tol=0.01
Num of Std Step Trials=20
Max Error Tol=0.3
Flow Tol Ratio=0.001
Split Flow NTrial=30
Split Flow Tol=0.02
Split Flow Ratio=0.02
Log Output Level=0
Friction Slope Method=1
Unsteady Friction Slope Method=2
Unsteady Bridges Friction Slope Method=1
Global Log Level=0
CheckData=False
Run HTab=0
Run UNet=0
Run PostProcess=0
UNET Theta=0
UNET Theta Warmup=0
UNET ZTol=0
UNET ZSATol=0
UNET MxIter=0
UNET MaxInSteps=0
UNET DtIC=0
UNET DtMin=0
UNET MaxCRTS=0
UNET WFStab=0
UNET SFStab=0
UNET WFX=0
UNET SFX=0
UNET DSS MLevel=0
UNET DZMax Abort=0
UNET Convert EG Bridges=0
UNET Use Existing IB Tables=0
UNET Froude Limit=0
UNET Froude Power=0
Write IC File=0
Echo Input=False
Echo Output=False
Write Detailed=0

--- RFBULLCR.f01 (steady flow) ---

Flow Title=NFF Regression Equation
Program Version=4.00
Number of Profiles=1
Profile Names=P100yr
River Rch & RM=RFBULLCR,Main      ,14807.5
     358
River Rch & RM=RFBULLCR,Main      ,13765.9
     379
River Rch & RM=RFBULLCR,Main      ,12581.7
     412
River Rch & RM=RFBULLCR,Main      ,12268.1
     467
River Rch & RM=RFBULLCR,Main      ,11066
     496
River Rch & RM=RFBULLCR,Main      ,9567.6
     547
River Rch & RM=RFBULLCR,Main      ,7478.6
     604
River Rch & RM=RFBULLCR,Main      ,7174.3
     672
River Rch & RM=RFBULLCR,Main      ,5666.4
     696
River Rch & RM=RFBULLCR,Main      ,1774.2
     759
Boundary for River Rch & Prof#=RFBULLCR,Main      ,1
Up Type=0
Dn Type=3
Dn Slope=0.006205

--- RFBULLCR.g01 (geometry) ---

Geom Title=USGS 10m DEM
Program Version=4.00

River Reach=RFBULLCR        ,Main
Reach XY= 30
     1563083.199      342464.711     1562811.258      342248.326
     1562218.863       342095.42      1561997.59      342108.125
     1561182.316      341231.654     1560998.598       341383.11
     1560453.211      341375.191     1559482.972      341137.031
     1559178.707       341310.43     1558982.499      341321.372
     1557946.643      341034.151     1557476.108      340712.079
     1557259.839      340676.579     1557078.729      340531.442
     1556975.304      339734.442     1556756.863      339746.902
     1556579.667       339646.03     1555888.433      339111.516
     1555355.635      339298.744     1554628.486      339820.126
      1554210.63       339652.79     1553746.552      339608.033
     1553455.356       339317.01     1553184.443      339342.097
     1552928.536      339184.475     1552438.225      339027.145
     1552160.275      338864.501     1551712.676      338456.867
       1551454.2      338632.065     1551153.607      339054.802

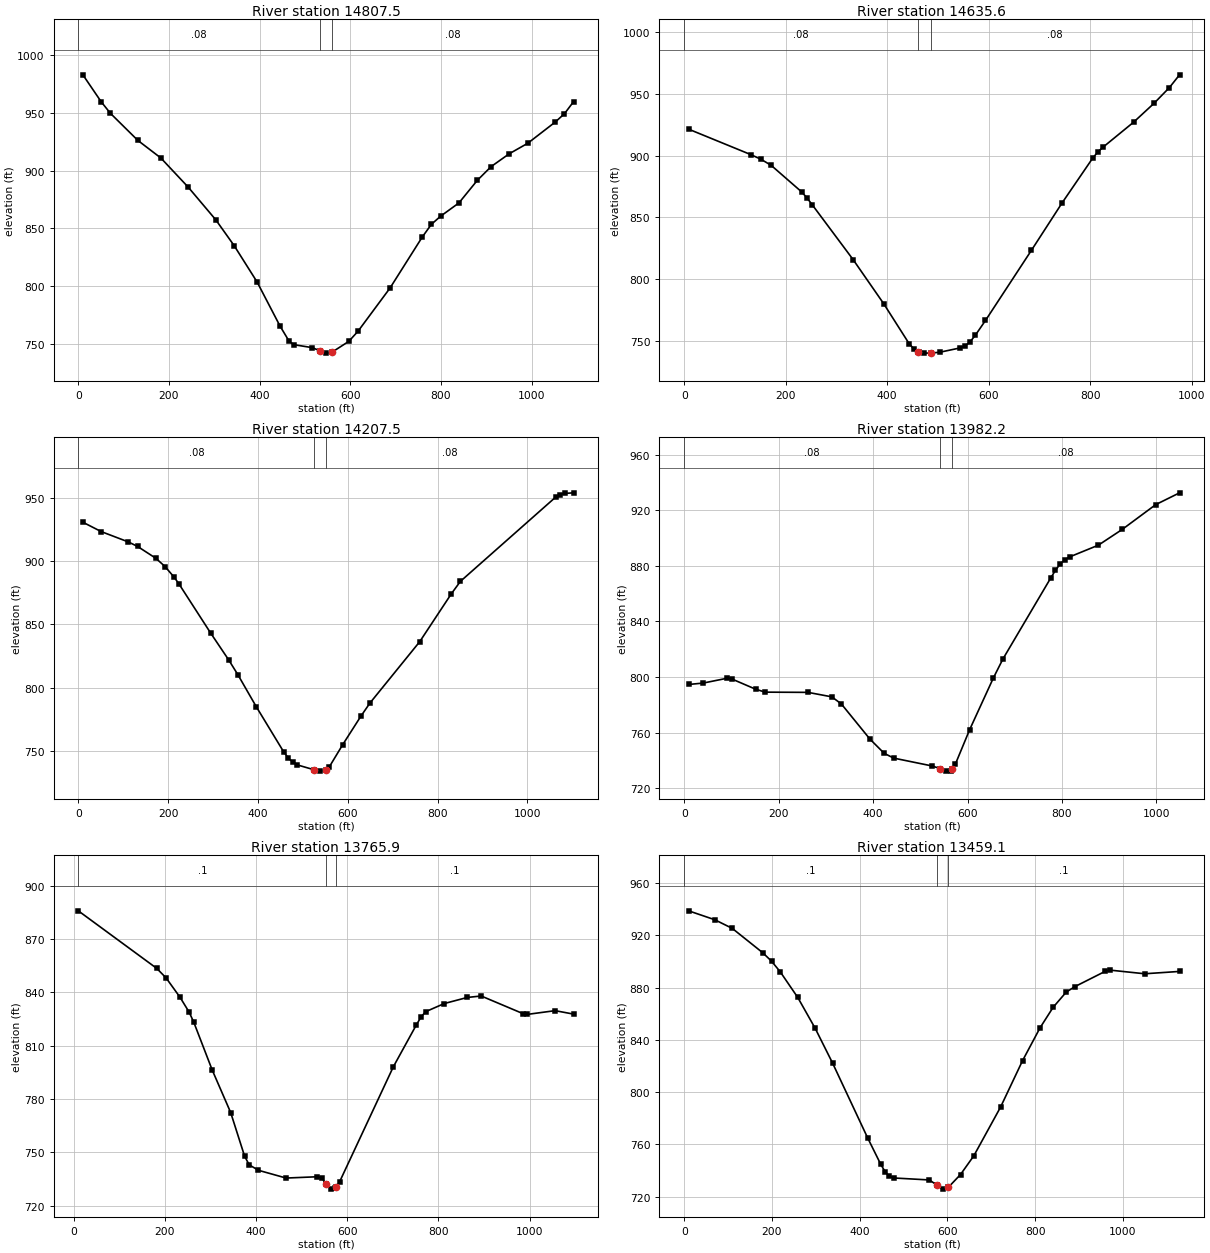
Type RM Length L Ch R = 1 ,14807.5 ,178.1,171.9,166.8
XS GIS Cut Line= 3
     1563475.153      342084.594      1563076.37      342457.406
     1562692.198      342846.114
#Sta/Elev= 30
    10.1     983    50.5  959.63    70.8  949.64   131.4  926.13     182  910.94
   242.6  885.55   303.3  857.29   343.7  834.97   394.3  803.47   444.8  765.32
     465  752.06   475.1  749.15   515.6  746.59   533.4   743.8   545.9  741.81
   558.4  742.36   596.5  751.99   616.8  760.74   687.6   798.3   758.4  842.33
   778.7  853.44   798.9  860.45   839.4  871.97   879.9  891.53   910.3  903.43
   950.7  914.67   991.2  923.68  1051.9   942.1  1072.2  949.32  1092.4  959.84
#Mann= 3 , 0 , 0
       0     .08       0   533.4    .045       0   558.4     .08       0
Bank Sta=533.4,558.4
XS Rating Curve= 0 ,0
Exp/Cntr=0.3,0.1

Type RM Length L Ch R = 1 ,14635.6 ,432.7,428.1,423
XS GIS Cut Line= 4
     1563166.643      341910.557     1563013.532      342250.803
     1562890.193      342433.685     1562635.009      342718.641
#Sta/Elev= 30
    10.1  921.18   131.1  900.83   151.3  897.02   171.4   892.1   231.9  870.42
     242  865.66   252.1  860.27   332.8  815.77   393.2  779.97   443.3   747.6
   453.3  743.03   460.9   741.2   463.3  740.62   473.4  739.97   485.9  740.03
   503.5  740.68   543.6  744.17   553.6   745.7   563.6  749.26   573.6  754.39
   593.7  766.42   684.3   823.3   744.7  861.68   805.1  898.01   815.2     903
   825.2  906.77   885.6  927.07   925.9  942.37   956.1  955.08   976.2  965.45
#Mann= 3 , 0 , 0
       0     .08       0   460.9    .045       0   485.9     .08       0
Bank Sta=460.9,485.9
XS Rating Curve= 0 ,0
Exp/Cntr=0.3,0.1

Type RM Length L Ch R = 1 ,14207.5 ,235.3,225.4,215.9
XS GIS Cut Line= 3
     1562798.763      341688.342     1562572.997       342188.19
     1562353.614      342697.419
#Sta/Elev= 30
    10.2  930.63    50.8  923.29   111.7  915.05     132  911.53   172.7  902.19
     193  895.71   213.3   887.3   223.5   882.3   294.5   843.3   335.2  821.83
   355.5  810.22   396.1  785.18   457.1  749.58   467.2  744.76   477.4  741.43
   487.5  739.19   525.8  735.26   538.3  734.27   550.8   735.2   558.6  737.47
   588.8   755.2   629.1  777.56   649.3  787.96   760.2  836.41   830.7  874.24
   850.9  884.03  1062.6  950.37  1072.7  952.49  1082.8  953.38  1102.9  953.84
#Mann= 3 , 0 , 0
       0     .08       0   525.8    .045       0   550.8     .08       0
Bank Sta=525.8,550.8
XS Rating Curve= 0 ,0
Exp/Cntr=0.3,0.1

Type RM Length L Ch R = 1 ,13982.2 ,224.2,216.3,208.4
XS GIS Cut Line= 4
     1562477.645      341591.577     1562367.065      342021.137
     1562350.053      342272.069     1562324.535      342625.073
#Sta/Elev= 30
    10.1  794.63    40.3  795.63    90.7  799.09   100.8  798.57   151.2   791.2
   171.4  789.08   262.1  788.92   312.5   785.7   332.7  780.61   393.2   755.3
   423.4  745.04   443.6  741.58     524  735.98   541.7  734.09   554.2   732.2
   564.3  732.57   566.7   733.7   574.3  737.29   604.5  762.09   654.8  799.38
     675  813.01     776   871.2   786.1  876.79   796.2  881.43   806.3  884.53
   816.4  886.51   877.1  894.94   927.7   906.3   998.4  924.11    1049  932.63
#Mann= 3 , 0 , 0
       0     .08       0   541.7    .045       0   566.7     .08       0
Bank Sta=541.7,566.7
XS Rating Curve= 0 ,0
Exp/Cntr=0.3,0.1

Type RM Length L Ch R = 1 ,13765.9 ,278.9,306.7,334.6
XS GIS Cut Line= 4
     1562251.446      341550.298     1562128.893      341999.872
      1562179.93      342229.538     1562065.097      342608.061
#Sta/Elev= 30
    10.1  885.77   182.3  853.37   202.6  848.06     233  837.25   253.2  828.81
   263.4  823.14   303.9  796.21   344.4   772.3   374.8  747.86   384.9  742.93
   405.2  739.84     466  735.47   534.6   736.2   544.4  735.43   554.2  732.06
     564  729.24   573.8  729.62   576.5  730.69   583.6   733.5   701.2  798.03
     752  821.73   762.1  826.11   772.2  829.04   812.8  833.61   863.5  837.05
     894  837.87   985.2     828   995.4  827.53  1056.2  829.62  1096.8  827.67
#Mann= 3 , 0 , 0
    10.1      .1       0   554.2    .045       0   576.5      .1       0
Bank Sta=554.2,576.5
XS Rating Curve= 0 ,0
Exp/Cntr=0.3,0.1

Type RM Length L Ch R = 1 ,13459.1 ,450.7,451.6,453
XS GIS Cut Line= 4
     1562145.906      341468.238     1561975.783      341914.811
     1561784.394      342110.452     1561563.235      342416.673
#Sta/Elev= 30
      10  938.83    69.7     932   109.5  925.38   179.2  906.67   199.1  900.24
     219  892.06   258.9  872.44   298.7  848.74   338.5  822.01   418.1  764.95
     448  744.67     458  738.98   467.9  735.43   477.9  734.19     559  732.67
   576.9  728.55   589.4  725.65   601.9  726.95   629.9  736.84   660.3  751.21
   721.2  788.48   771.4  824.11   811.2   849.2     841   864.9   870.9  876.57
   890.7  880.77   960.3  892.57   970.3  893.43  1049.8  890.62  1129.3  892.41
#Mann= 3 , 0 , 0
       0      .1       0   576.9    .045       0   601.9      .1       0
Bank Sta=576.9,601.9
XS Rating Curve= 0 ,0
Exp/Cntr=0.3,0.1

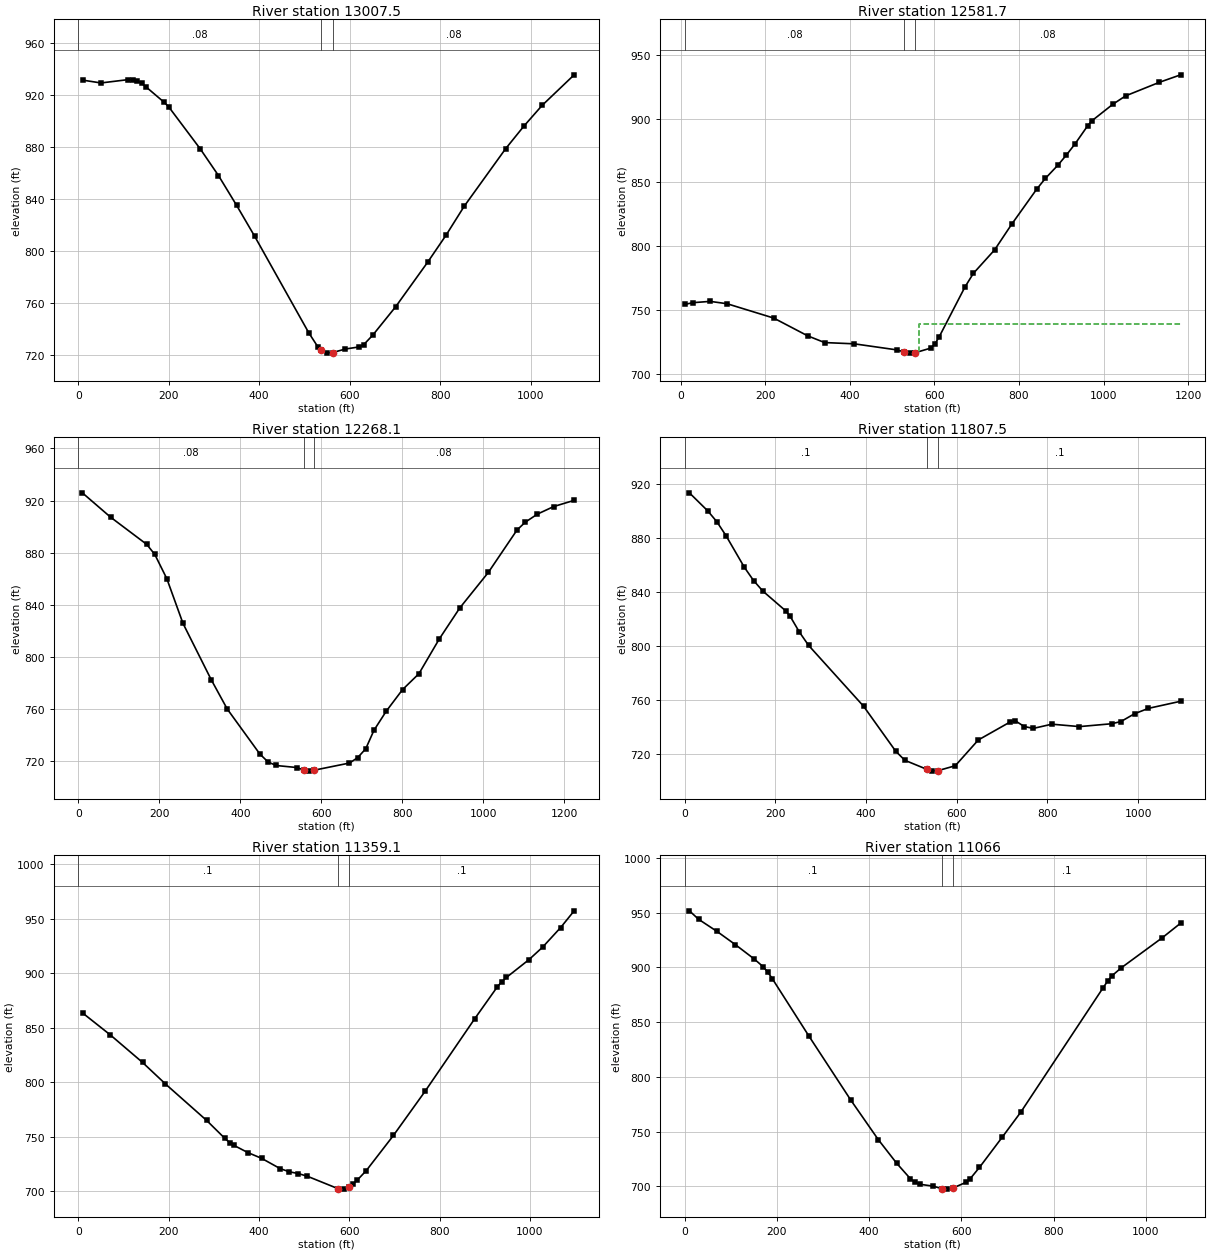
Type RM Length L Ch R = 1 ,13007.5 ,422.6,425.8,428.5
XS GIS Cut Line= 3
     1561993.008      341289.158       1561598.1      341671.787
     1561198.589      342044.864
#Sta/Elev= 30
      10  931.37      50  929.22     110  931.76     120  931.79     130  930.81
     140  928.91     150  926.09     190  914.27     200  910.77   269.9  878.35
   309.9  857.96   349.9   835.1   389.9  811.26   509.9  736.78   529.9  726.06
   537.4   723.6   549.9  721.32   562.4  721.76   590.4  724.47   620.7  726.08
   630.9  727.77   651.1  735.15   701.7  756.99   772.6  791.33   813.1  812.02
   853.5  834.42   944.7   878.5   985.1   895.9  1025.6  911.93  1096.5  935.47
#Mann= 3 , 0 , 0
       0     .08       0   537.4    .045       0   562.4     .08       0
Bank Sta=537.4,562.4
XS Rating Curve= 0 ,0
Exp/Cntr=0.3,0.1

Type RM Length L Ch R = 1 ,12581.7 ,368,313.6,259.3
XS GIS Cut Line= 4
     1561644.043      340928.098     1561393.112      341302.368
     1561193.218      341455.479     1561086.891      341923.317
#Sta/Elev= 30
      10  754.45      30  755.79    70.1  756.78   110.1  754.92   220.3  743.69
   300.4  729.79   340.5   724.5   410.6  723.51     511  718.77   528.8  717.12
   541.3  716.22   553.8  716.46   591.6  720.18   601.7  723.62   611.8  729.25
   672.2  767.98   692.3  778.77   742.4  797.13   782.4  817.05   842.3   844.9
   862.3  853.11   892.3  863.63   912.3  871.55   932.3  880.08   962.3  894.34
   972.3  898.29  1022.2  911.34  1052.2  917.86  1132.2  928.52  1182.2  934.35
#Mann= 3 , 0 , 0
      10     .08       0   528.8    .045       0   553.8     .08       0
#XS Ineff= 2 , 0
                          563.94          738.79
Permanent Ineff=
       F       F
Bank Sta=528.8,553.8
XS Rating Curve= 0 ,0
Exp/Cntr=0.3,0.1

Type RM Length L Ch R = 1 ,12268.1 ,433.6,460.6,488.7
XS GIS Cut Line= 4
     1560848.719      340809.012     1560916.768      341170.523
     1561205.977      341353.405     1561074.132      341851.014
#Sta/Elev= 30
     9.9   925.9    79.5  907.26     169  886.33   188.9  878.61   218.7  859.96
   258.5  825.74   328.1  782.61   367.9  759.99   448.4   725.5   468.5  719.44
   488.6  716.69     539  715.15   556.6  713.28   569.1  712.37   581.6  713.03
   669.8  718.58   689.9  722.68     710  729.55   730.2  743.66   760.5  758.31
   800.9  774.93   841.3  787.11   891.7  813.82   942.2  837.54  1012.9  864.88
  1083.5  897.31  1103.7  903.29    1134  909.57  1174.4  915.39  1224.8  920.12
#Mann= 3 , 0 , 0
       0     .08       0   556.6    .045       0   581.6     .08       0
Bank Sta=556.6,581.6
XS Rating Curve= 0 ,0
Exp/Cntr=0.3,0.1

Type RM Length L Ch R = 1 ,11807.5 ,438.6,448.5,457.1
XS GIS Cut Line= 3
     1560658.012      340810.996     1560680.246      341356.612
     1560677.867      341904.406
#Sta/Elev= 30
    10.1  913.46    50.6  900.08    70.8     892      91  881.65   131.5   858.2
   151.7  848.46   171.9  840.72   222.5     826   232.6  821.84   252.8  810.24
     273  800.42   394.4  755.27   465.2  721.98   485.4  715.21   533.6  708.55
   546.1  707.16   558.6  707.52   596.8  711.17   647.5  730.25   718.5  743.73
   728.7  744.56     749   740.2   769.2  738.85   809.8  741.96   870.7  740.17
   941.7  742.28     962  743.89   992.4  749.73  1022.9  753.69  1093.9  758.95
#Mann= 3 , 0 , 0
       0      .1       0   533.6    .045       0   558.6      .1       0
Bank Sta=533.6,558.6
XS Rating Curve= 0 ,0
Exp/Cntr=0.3,0.1

Type RM Length L Ch R = 1 ,11359.1 ,309.6,293.1,276
XS GIS Cut Line= 3
     1560424.686      340771.452     1560266.048      341264.091
      1560084.01      341815.278
#Sta/Elev= 30
    10.1  863.31      71  843.37   142.1  818.25   192.8  798.54   284.1   765.1
   324.7  748.54   334.9  744.83     345  742.16   375.5  735.62   405.9  730.36
   446.5  721.05   466.8  718.08   487.1  716.43   507.4  713.92   575.1  702.59
   587.6  702.16   600.1  704.33   607.6  706.57   617.6   710.4   637.6  719.11
   697.7  751.29   767.8  791.74   877.8  858.27   927.9  887.49   937.9  892.28
   947.9  896.04   997.9  912.37    1028  923.76    1068  941.75    1098   957.1
#Mann= 3 , 0 , 0
       0      .1       0   575.1    .045       0   600.1      .1       0
Bank Sta=575.1,600.1
XS Rating Curve= 0 ,0
Exp/Cntr=0.3,0.1

Type RM Length L Ch R = 1 ,11066   ,401.5,411.7,421.8
XS GIS Cut Line= 4
     1559972.586      340702.685     1559955.574      341162.017
     1560027.876      341421.454     1559989.598      341765.953
#Sta/Elev= 30
      10  951.64      30  943.88    69.9  932.83   109.9  920.69   149.9  907.87
   169.9  900.64   179.9  895.72   189.9  889.61   269.8  836.88   359.7  779.01
   419.7  742.68   459.6  721.08   489.6  706.84   499.5  703.64   509.5  701.91
   539.4  700.11   556.9  697.95   569.4  697.44   581.9  698.49   609.3  703.52
   619.2  706.99   639.2  717.26   689.1  745.16     729  767.83   907.2  881.22
   917.1  887.37     927  892.44   946.8  899.57    1036  927.11  1075.6  940.36
#Mann= 3 , 0 , 0
       0      .1       0   556.9    .045       0   581.9      .1       0
Bank Sta=556.9,581.9
XS Rating Curve= 0 ,0
Exp/Cntr=0.3,0.1

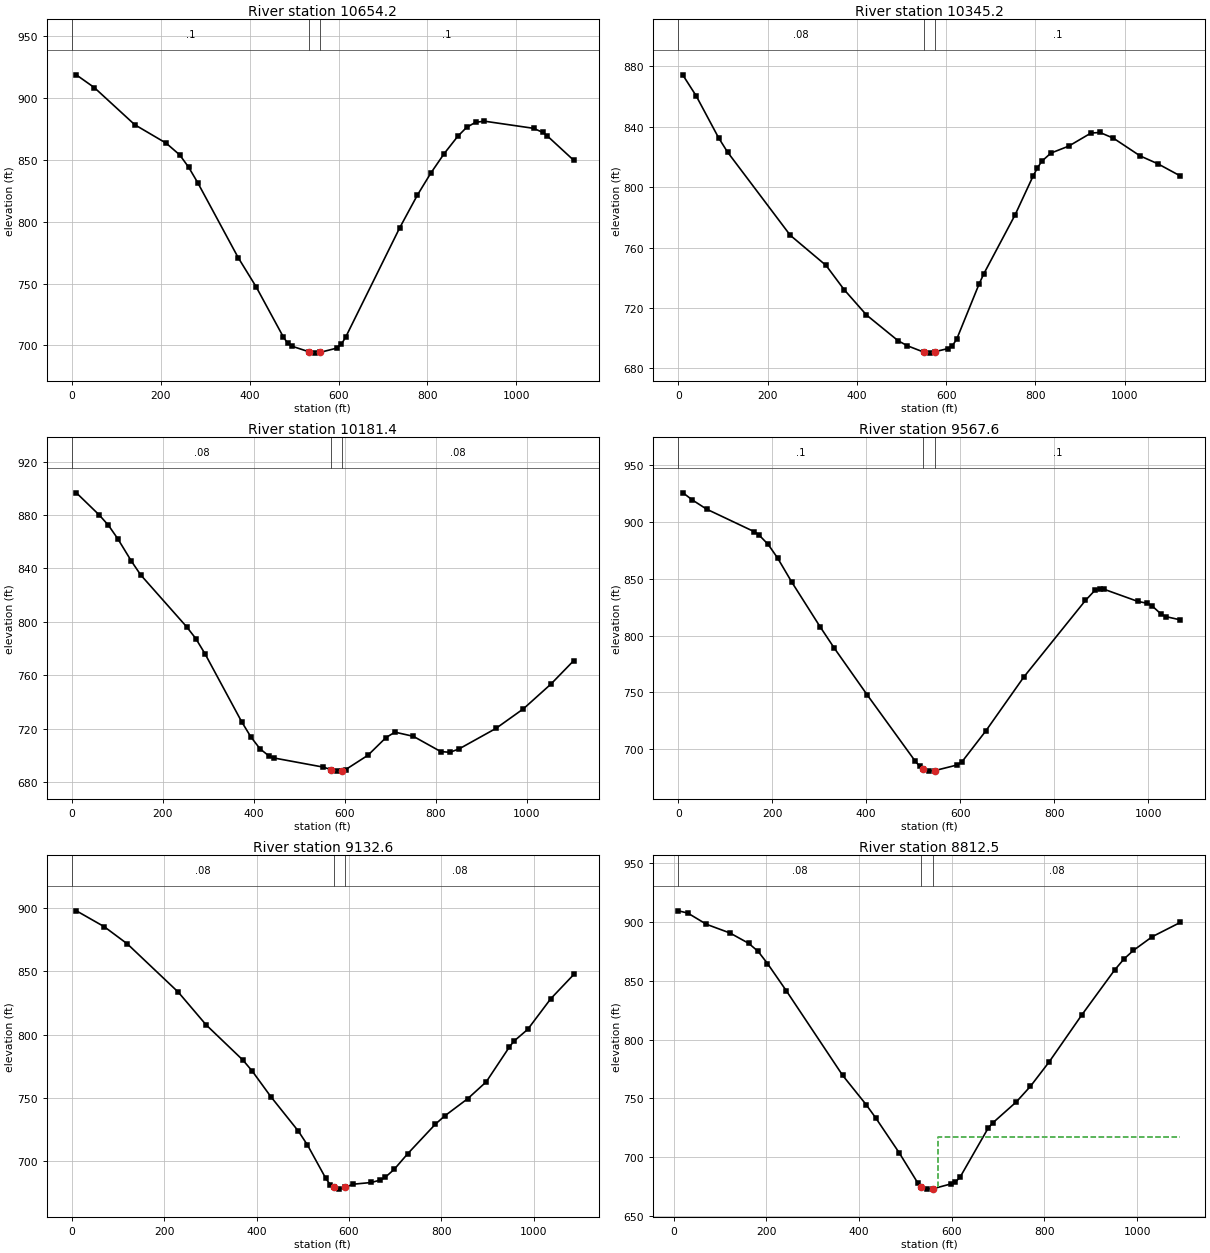
Type RM Length L Ch R = 1 ,10654.2 ,329.6,309.1,289.1
XS GIS Cut Line= 3
     1559666.705      340629.787     1559602.569      341162.017
     1559553.892      341753.192
#Sta/Elev= 30
    10.1  918.71    50.6  908.43   141.6   878.4   212.4  863.46   242.8  853.99
     263  843.97   283.2  831.61   374.2  771.04   414.7  747.37   475.4  707.17
   485.5   701.8   495.6  699.35   533.6  694.86   546.1  693.79   558.6  694.42
   596.4  697.86   606.5  701.01   616.5  707.02   737.2  794.79   777.4  821.51
   807.5  839.24   837.7  855.06   867.9  868.89     888  876.22   908.1  880.32
   928.2  881.25  1038.8  875.47  1058.9  872.26  1068.9  869.55  1129.3  849.55
#Mann= 3 , 0 , 0
       0      .1       0   533.6    .045       0   558.6      .1       0
Bank Sta=533.6,558.6
XS Rating Curve= 0 ,0
Exp/Cntr=0.3,0.1

Type RM Length L Ch R = 1 ,10345.2 ,153.7,163.8,173.9
XS GIS Cut Line= 4
      1559251.22      340671.258     1559229.955      341092.312
      1559417.09      341343.243     1559463.874      341730.272
#Sta/Elev= 30
      10  874.38    40.2  860.44    90.3  832.73   110.4  823.24   250.9  768.14
   331.2  748.13   371.4  732.19   421.6  715.35   492.3  698.34   512.5  695.06
   550.5   690.7     563   690.1   575.5  691.09   603.3  693.06   613.4  694.79
   623.5   699.2     674     736   684.1  742.48   754.6  781.73   794.6  807.25
   804.6  812.84   814.6  817.24   834.6  822.55   874.6  827.18   924.5  835.83
   944.5   836.2   974.5  832.46  1034.5  820.69  1074.5  815.43  1124.5  807.42
#Mann= 3 , 0 , 0
       0     .08       0   550.5    .045       0   575.5      .1       0
Bank Sta=550.5,575.5
XS Rating Curve= 0 ,0
Exp/Cntr=0.3,0.1

Type RM Length L Ch R = 1 ,10181.4 ,600.3,613.8,627.1
XS GIS Cut Line= 4
     1559032.657       340736.71     1559135.929      341158.241
     1559222.522      341420.566     1559197.053      341812.779
#Sta/Elev= 30
    10.1   896.6    60.6  879.94    80.7  872.26   100.9  862.35   131.2  845.41
   151.4  835.22   252.3  796.42   272.5  787.59   292.7  776.25   373.4  725.31
   393.6  713.98   413.8  705.05     434  699.58   443.9  698.27   552.4  691.43
   569.5  689.57     582  688.41   594.5  688.71   601.7  689.52     651  700.33
   690.5  713.51   710.2  717.56   750.6  714.45     811     703   831.2  702.51
   851.3  705.07     932  720.34   992.4  735.01  1052.9  753.51  1103.3  771.16
#Mann= 3 , 0 , 0
       0     .08       0   569.5    .045       0   594.5     .08       0
Bank Sta=569.5,594.5
XS Rating Curve= 0 ,0
Exp/Cntr=0.3,0.1

Type RM Length L Ch R = 1 ,9567.6  ,427.5,435.1,442.4
XS GIS Cut Line= 3
     1558688.159      340672.914       1558605.3      341200.045
     1558518.036      341727.675
#Sta/Elev= 30
    10.1  925.69    30.2  919.36    60.4  911.32   161.1  891.59   171.2  888.83
   191.3  880.28   211.4  868.29   241.6  847.05     302  807.64   332.2  788.82
   402.7  747.38   503.4  689.85   513.5  684.85   521.1  682.45   533.6  680.56
   546.1  681.05   594.1  686.03   604.2  689.01   654.7  716.07   735.4  763.46
   866.6  830.95   886.8  839.85   896.9  841.39     907  840.62   977.6   830.1
   997.8  828.41  1007.9  826.26    1028  818.71  1038.1  816.61  1068.4  813.81
#Mann= 3 , 0 , 0
       0      .1       0   521.1    .045       0   546.1      .1       0
Bank Sta=521.1,546.1
XS Rating Curve= 0 ,0
Exp/Cntr=0.3,0.1

Type RM Length L Ch R = 1 ,9132.6  ,317.7,320.1,323.8
XS GIS Cut Line= 4
     1558420.215      340587.852      1558233.08      341008.906
       1558122.5      341251.331     1558020.426       341595.83
#Sta/Elev= 30
      10  897.71    70.1  885.22   120.2  871.62   230.4  833.55   290.5  807.78
   370.6  779.78   390.7  771.11   430.7  751.04   490.4  723.77   510.1  712.82
   549.6  686.57   559.5  681.37   566.7   679.4   579.2  678.01   591.7  679.47
   608.8  681.88   648.3  683.26     668   685.2   677.9  687.21   697.6  693.57
   727.2  706.06   787.1  729.37   807.1   735.8     857  749.45   896.9  762.69
   946.8  790.11   956.8   794.8   986.7  804.14  1036.6  828.34  1086.5   847.5
#Mann= 3 , 0 , 0
       0     .08       0   566.7    .045       0   591.7     .08       0
Bank Sta=566.7,591.7
XS Rating Curve= 0 ,0
Exp/Cntr=0.3,0.1

Type RM Length L Ch R = 1 ,8812.5  ,336.5,338.3,338.6
XS GIS Cut Line= 3
     1558155.254      340524.622     1557886.748      341001.289
     1557594.208      341462.078
#Sta/Elev= 30
    10.1  909.37    30.4  907.53    70.9  897.93   121.6  890.55   162.1  881.73
   182.4  874.89   202.6  864.58   243.2  841.44   364.7  769.54   415.4  744.66
   435.6  733.63   486.3  703.96   526.8  678.08   534.6  675.09   547.1  672.88
   559.6  673.23   597.6  677.23   607.7  678.92   617.8  682.95   678.5  724.73
   688.6  729.23   739.1  746.94   769.5  760.16   809.9  780.91   880.6  820.99
   951.4  859.17   971.6  868.52   991.8  875.75  1032.3  887.37  1092.9  899.52
#Mann= 3 , 0 , 0
    10.1     .08       0   534.6    .045       0   559.6     .08       0
#XS Ineff= 2 , 0
                          569.53          717.12
Permanent Ineff=
       F       F
Bank Sta=534.6,559.6
XS Rating Curve= 0 ,0
Exp/Cntr=0.3,0.1

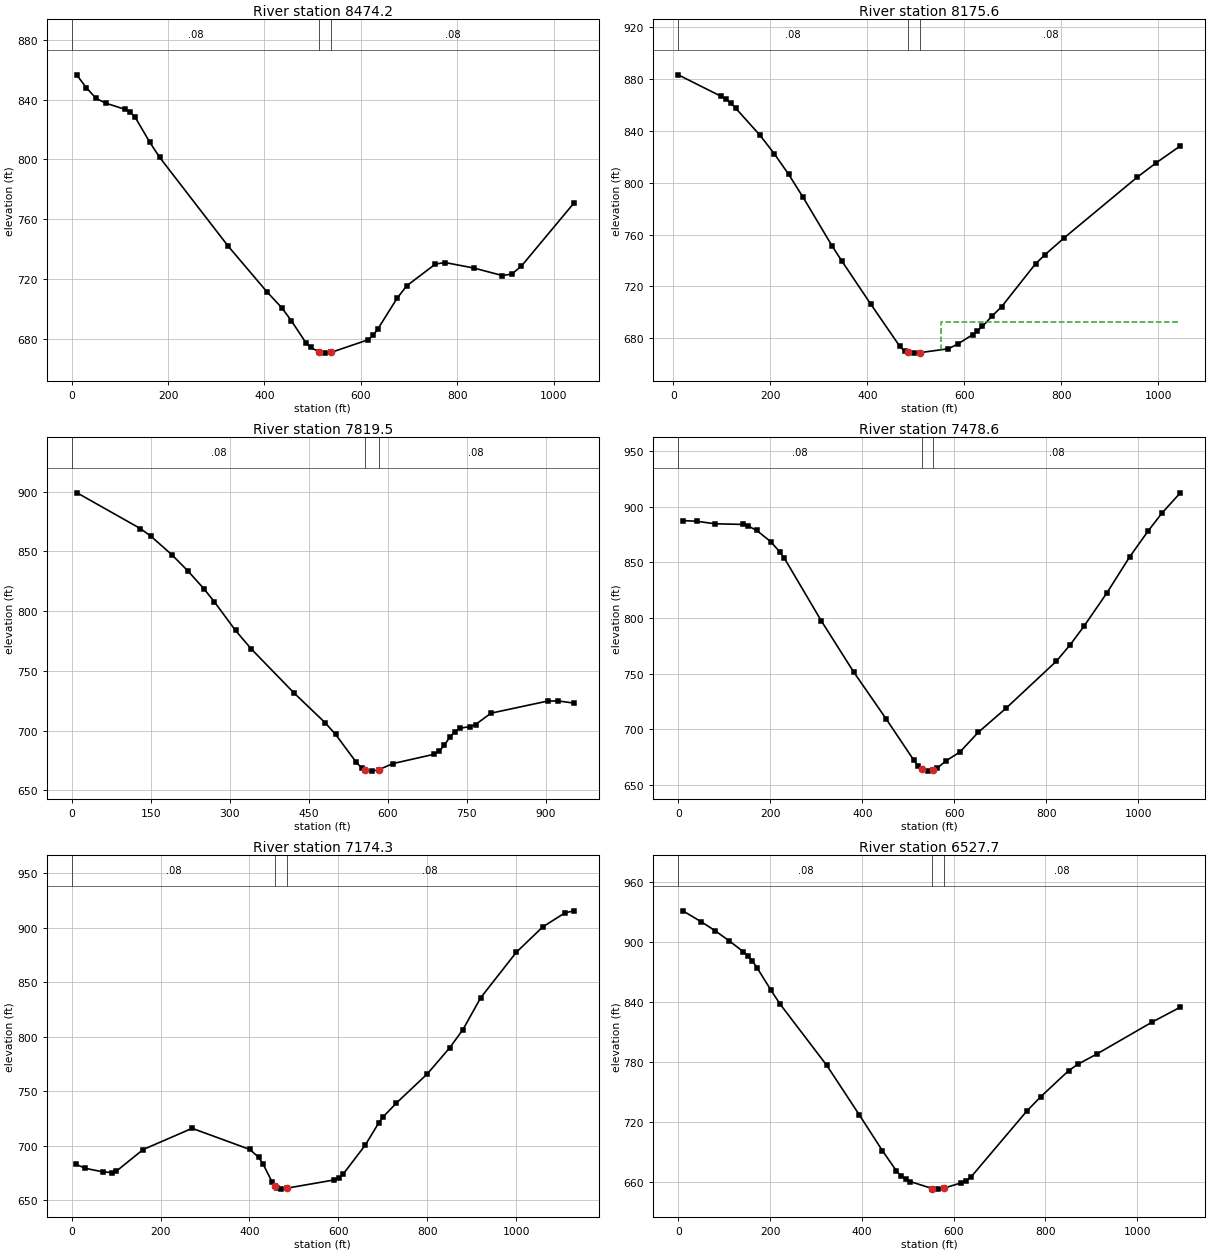
Type RM Length L Ch R = 1 ,8474.2  ,314.2,298.6,283
XS GIS Cut Line= 4
     1557880.075      340362.439     1557667.421      340719.698
     1557514.311      340953.616     1557322.923      341242.825
#Sta/Elev= 30
    10.1  856.63    30.4  847.93    50.7  840.82      71  837.61   111.5  833.46
   121.7  831.58   131.8  828.12   162.2  811.39   182.5  801.38   324.5  742.06
   405.6  711.29   435.7   700.9   455.7  692.17   485.7  677.53   495.6  674.24
   513.1  671.38   525.6  670.47   538.1  670.96   615.5  679.43   625.4  682.31
   635.4  686.68   675.4  707.25   695.3  715.53   754.8  730.04   774.6  731.07
   834.1  727.43   893.5  722.38   913.3  723.37   933.1  728.63  1042.1  770.79
#Mann= 3 , 0 , 0
       0     .08       0   513.1    .045       0   538.1     .08       0
Bank Sta=513.1,538.1
XS Rating Curve= 0 ,0
Exp/Cntr=0.3,0.1

Type RM Length L Ch R = 1 ,8175.6  ,318.3,356.1,393.9
XS GIS Cut Line= 4
     1557484.539      340222.088     1557348.441      340562.334
     1557344.188      340872.808     1557222.185      341220.154
#Sta/Elev= 30
     9.9  883.34      99  866.61   108.9  864.36   118.9  861.21   128.8   857.4
   178.3  836.76     208  822.41   237.7  806.44   267.4  788.75   326.8  751.45
   346.6  739.94   406.5  706.53   466.6   673.8   476.6  670.04   484.2  668.99
   496.7   668.5   509.2  668.93   566.8  671.85   586.8  675.63   616.9  682.77
   626.9  685.65   636.9  689.08   656.9  697.09     677  704.49   746.6  737.46
   766.5  744.61   806.3  757.69   955.6  804.12   995.4  815.41  1045.1  828.46
#Mann= 3 , 0 , 0
     9.9     .08       0   484.2    .045       0   509.2     .08       0
#XS Ineff= 2 , 0
                          551.61          692.64
Permanent Ineff=
       F       F
Bank Sta=484.2,509.2
XS Rating Curve= 0 ,0
Exp/Cntr=0.3,0.1

Type RM Length L Ch R = 1 ,7819.5  ,338.3,340.9,343.4
XS GIS Cut Line= 4
     1557514.311      340149.786     1557161.306      340477.272
      1556931.64      340532.562     1556782.783      340715.444
#Sta/Elev= 30
      10  898.95   130.4  869.02   150.5   862.6   190.6  846.94   220.7  833.55
   250.8  818.75   270.9  807.71     311  783.78   341.1  768.23   421.3  731.85
   481.5  706.45   501.2  696.74   540.6  673.33   550.4  668.89   557.6  667.23
   570.1  666.09   582.6  667.16   609.5  672.36   688.2   680.2   698.1  682.87
   707.9  687.89   717.7  694.38   727.6   699.1   737.4  702.01     757  703.38
   766.9   705.1   796.3  714.59   904.4  724.77   924.1   724.8   953.6  723.02
#Mann= 3 , 0 , 0
       0     .08       0   557.6    .045       0   582.6     .08       0
Bank Sta=557.6,582.6
XS Rating Curve= 0 ,0
Exp/Cntr=0.3,0.1

Type RM Length L Ch R = 1 ,7478.6  ,304.9,304.4,302.9
XS GIS Cut Line= 3
     1557562.859      340082.954     1556927.387      340175.304
     1556493.574      340290.137
#Sta/Elev= 30
      10  887.65    40.1  887.05    80.3  884.77   140.5  884.22   150.5  883.14
   170.6  878.75   200.7  868.84   220.7  859.48   230.8   853.7     311  797.46
   381.3  751.58   451.5  709.64   511.7  672.48   521.7  666.92   529.3  664.36
   541.8  662.57   554.3  663.21   561.9  664.97   581.9  671.86     612  679.75
   652.1  697.51     712  718.98   821.6  761.32   851.6  776.08   881.5  792.67
   931.3  822.62   981.2  855.26  1021.1  878.38    1051  894.36  1090.9  912.59
#Mann= 3 , 0 , 0
       0     .08       0   529.3    .045       0   554.3     .08       0
Bank Sta=529.3,554.3
XS Rating Curve= 0 ,0
Exp/Cntr=0.3,0.1

Type RM Length L Ch R = 1 ,7174.3  ,675.9,646.6,616
XS GIS Cut Line= 4
     1557386.719      339643.671     1557203.837      339843.565
     1556816.807      339890.349     1556454.245      340188.348
#Sta/Elev= 30
      10  683.07    30.1  679.52    70.2  676.18    90.3  675.63   100.3  676.85
   160.6  696.66   270.9  716.11   400.9  696.74   420.9  689.38   430.9  683.19
   450.9  666.91   458.4  662.99   460.9  661.69   470.9   660.4   483.4  661.23
   590.8  668.83   600.8  670.51   610.8  674.09   660.8  700.85   690.7  720.92
   700.7  726.53   730.7  739.25   800.6  766.14   850.5  789.81   880.5  806.57
   920.4  835.73  1000.3  877.25  1060.2  900.68  1110.1  913.49  1130.1  915.37
#Mann= 3 , 0 , 0
       0     .08       0   458.4    .045       0   483.4     .08       0
Bank Sta=458.4,483.4
XS Rating Curve= 0 ,0
Exp/Cntr=0.3,0.1

Type RM Length L Ch R = 1 ,6527.7  ,319.3,329.2,338.6
XS GIS Cut Line= 3
     1556765.425      339090.579     1556537.149      339586.721
     1556288.476      340075.016
#Sta/Elev= 30
    10.1  930.88    50.6  919.82    80.9  910.87   111.3  900.82   141.6  890.16
   151.7  886.17   161.8  880.74   171.9  873.94   202.3  851.46   222.5  837.39
   323.6   776.6   394.4  727.29     445  691.32   475.3  671.35   485.5  666.14
   495.6  662.66   505.7  660.55   553.9  653.49   566.4  652.99   578.9  653.96
   617.2  659.33   627.3  661.38   637.5  664.86   759.2  730.72   789.7  745.14
   850.6  771.21   870.9  777.69   911.5  787.73  1033.2  819.92  1094.1  834.66
#Mann= 3 , 0 , 0
       0     .08       0   553.9    .045       0   578.9     .08       0
Bank Sta=553.9,578.9
XS Rating Curve= 0 ,0
Exp/Cntr=0.3,0.1

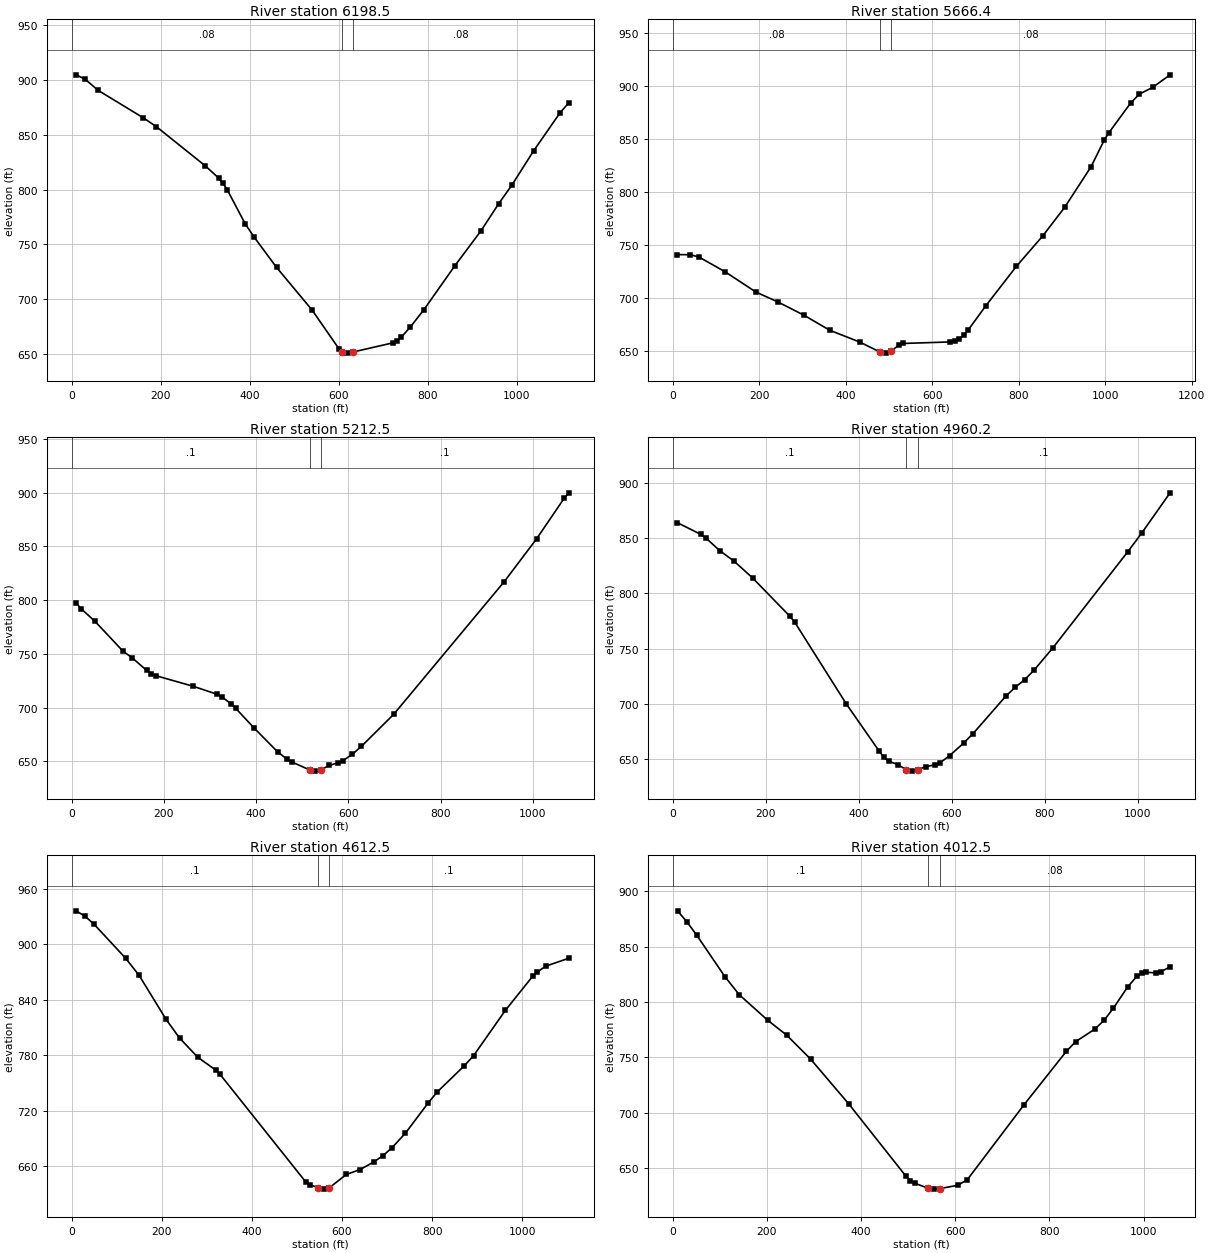
Type RM Length L Ch R = 1 ,6198.5  ,556.5,532.1,508.7
XS GIS Cut Line= 4
     1556438.284      338861.105     1556310.692      339375.727
     1556093.785      339584.128     1555936.421        339822.3
#Sta/Elev= 30
      10  904.73      30  900.88      60  890.49   160.1  865.74   190.1  857.53
   300.1  821.69   330.1   810.6   340.1  805.67   350.1  799.41   390.1  768.56
   410.2  756.45   460.2     729   540.2  689.93   600.4  654.59   607.9  652.01
   610.4  651.15   620.4  650.67   632.9  651.79   720.7  659.98   730.7  661.81
   740.8  665.48   760.8  674.58   790.9  690.19   860.5  730.38   919.6  762.52
     959  787.07   988.5  804.02  1037.7  835.49  1096.8   870.1  1116.5  879.23
#Mann= 3 , 0 , 0
       0     .08       0   607.9    .045       0   632.9     .08       0
Bank Sta=607.9,632.9
XS Rating Curve= 0 ,0
Exp/Cntr=0.3,0.1

Type RM Length L Ch R = 1 ,5666.4  ,462.1,453.9,446.5
XS GIS Cut Line= 4
     1555919.409      338627.186     1555842.854      338920.648
     1555868.372      339248.135     1555791.722      339760.619
#Sta/Elev= 30
    10.1  740.98    40.4  740.85    60.7   738.7   121.3  724.71   192.1   705.7
   242.6  696.42   303.3  683.83     363   669.6   432.7  658.44   479.9  648.96
   492.4  648.04   504.9  650.09   522.3  655.36   532.2  657.16   641.9   658.6
   652.1  659.41   662.2  661.38   672.4  664.82   682.6  669.57   723.2  692.34
   794.3  729.76   855.3  758.52   906.1  785.48   967.1  823.78   997.5  848.81
  1007.7  855.56  1058.5  883.81  1078.8  892.36  1109.3  898.65  1149.9  910.57
#Mann= 3 , 0 , 0
       0     .08       0   479.9    .045       0   504.9     .08       0
Bank Sta=479.9,504.9
XS Rating Curve= 0 ,0
Exp/Cntr=0.3,0.1

Type RM Length L Ch R = 1 ,5212.5  ,256,252.3,247.9
XS GIS Cut Line= 3
     1555243.171      338771.791     1555435.096      339264.011
     1555622.105       339780.73
#Sta/Elev= 30
    10.2  797.48    20.3  792.08    50.8  780.21   111.8  752.33   132.1  746.03
   162.6  734.62   172.7  731.63   182.9  729.63   264.2   719.7     315  712.41
   325.1  710.23   345.4  703.54   355.6  699.37   396.2  680.71     447  658.63
   467.4  651.85   477.5  649.33   515.8  642.04   528.3  640.84   540.8  642.08
   558.3  646.16   578.3  648.64   588.3  650.59   608.2  656.37   628.2  663.86
   698.2  693.68     938  817.24  1007.9  856.96  1067.8  894.75  1077.8  899.76
#Mann= 3 , 0 , 0
       0      .1       0   515.8    .045       0   540.8      .1       0
Bank Sta=515.8,540.8
XS Rating Curve= 0 ,0
Exp/Cntr=0.3,0.1

Type RM Length L Ch R = 1 ,4960.2  ,348.9,347.7,348.5
XS GIS Cut Line= 2
     1554966.721      338937.661     1555485.596      339873.336
#Sta/Elev= 30
    10.1  863.99    60.6  853.38    70.7  850.43   100.9  838.75   131.2  829.43
   171.6  814.08   252.3  779.19   262.4  773.96   373.5  699.91   444.1  657.26
   454.2  651.74   464.3  648.08   484.5  645.14   502.3   640.4   514.8  639.16
   527.3  640.56   545.1  643.25   565.2  644.98   575.3  646.78   595.5  653.12
   625.8  664.55     646  673.11   716.6  707.03   736.8  715.04     757  721.87
   777.2  730.51   817.6  750.63   979.1   837.8  1009.4  854.88  1069.9  891.04
#Mann= 3 , 0 , 0
       0      .1       0   502.3    .045       0   527.3      .1       0
Bank Sta=502.3,527.3
XS Rating Curve= 0 ,0
Exp/Cntr=0.3,0.1

Type RM Length L Ch R = 1 ,4612.5  ,581.6,600,617.1
XS GIS Cut Line= 3
     1554660.589      339132.232     1554952.822       339609.35
     1555203.433      340092.213
#Sta/Elev= 30
      10  936.16      30  930.31      50  921.68   119.9  885.01   149.9   866.5
   209.8  818.87   239.8  798.67   279.8  778.11   319.7  764.14   329.7  759.38
   519.5  643.39   529.5  640.06     547  637.21   559.5  635.48     572  636.95
   609.9  651.36   640.1  656.58   670.3  664.72   690.5  671.49   710.6  679.92
   740.8   695.9   791.2  728.51   811.4  740.43   871.8  768.88     892  779.62
   962.5  828.52  1022.9  865.23    1033  870.02  1053.2  876.54  1103.5  884.93
#Mann= 3 , 0 , 0
       0      .1       0     547    .045       0     572      .1       0
Bank Sta=547,572
XS Rating Curve= 0 ,0
Exp/Cntr=0.3,0.1

Type RM Length L Ch R = 1 ,4012.5  ,205.7,206.6,206.8
XS GIS Cut Line= 3
      1554510.17      339165.649     1554447.047      339717.051
     1554379.797      340213.582
#Sta/Elev= 30
    10.1  882.26    30.3  872.17    50.5  860.56     111  822.72   141.3  806.49
   201.8  783.46   242.2  769.95   292.6  748.51   373.4  708.18   494.5  643.13
   504.5  638.85   514.6  636.34   542.5  631.83     555  631.09   567.5  631.57
   605.1  634.55   625.2  639.43   745.4  706.91   835.6  755.33   855.6   764.2
   895.7  775.29   915.8  783.34   935.8  794.45   965.9  813.45   985.9  823.35
   995.9  826.01    1006  826.84    1026  826.22    1036  827.18  1056.1   831.7
#Mann= 3 , 0 , 0
       0      .1       0   542.5    .045       0   567.5     .08       0
Bank Sta=542.5,567.5
XS Rating Curve= 0 ,0
Exp/Cntr=0.3,0.1

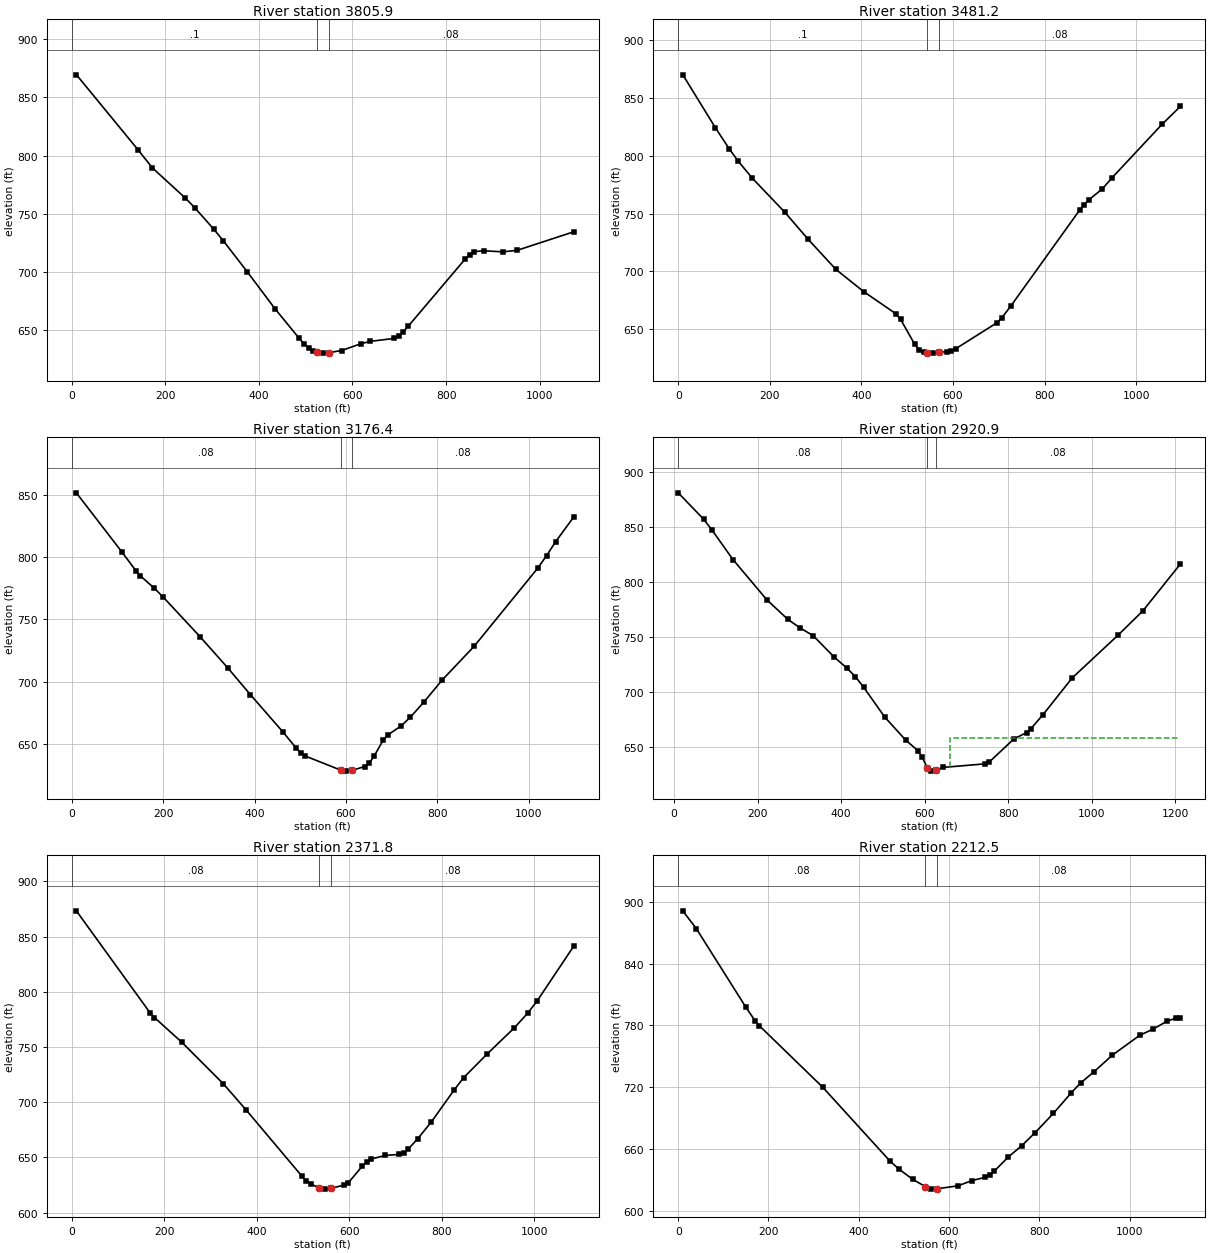
Type RM Length L Ch R = 1 ,3805.9  ,322.9,324.7,326.4
XS GIS Cut Line= 2
     1554320.254      339133.302      1554175.65       340196.57
#Sta/Elev= 30
    10.1  869.49   141.7  804.89   172.1  789.43     243  763.24   263.2  754.87
   303.7  736.46   323.9  726.54   374.6  700.07   435.3  667.51   485.9  642.61
     496  637.93   506.2  634.25   516.3  631.72     524  630.58   536.5  629.77
     549  630.18     577  632.03   617.5  637.83   637.8  639.88   688.4  642.42
   698.5  644.64   708.6  648.24   718.7  652.75   840.2  710.52   850.3  714.66
   860.5  717.25   880.7  717.94   921.2  717.02   951.6  718.29  1073.1   734.3
#Mann= 3 , 0 , 0
       0      .1       0     524    .045       0     549     .08       0
Bank Sta=524,549
XS Rating Curve= 0 ,0
Exp/Cntr=0.3,0.1

Type RM Length L Ch R = 1 ,3481.2  ,293.3,304.9,316.4
XS GIS Cut Line= 3
     1554037.343         339093.     1553928.972      339618.152
     1553818.629      340167.373
#Sta/Elev= 30
    10.1  869.63    80.9  824.13   111.3  805.81   131.5  794.87   161.9   780.4
   232.7  751.11   283.3  727.92     344   701.9   404.7   682.7   475.5  663.45
   485.6  658.66     516  637.47   526.1  632.45   536.2  630.35   543.7   629.8
   556.2  629.55   568.7  630.33   586.2  630.66   596.2  631.48   606.2  633.39
   696.3  655.83   706.3  659.89   726.3  670.21   876.3  752.79   886.3  757.56
   896.3  761.71   926.4  771.32   946.4  780.43  1056.4  826.91  1096.4  842.33
#Mann= 3 , 0 , 0
       0      .1       0   543.7    .045       0   568.7     .08       0
Bank Sta=543.7,568.7
XS Rating Curve= 0 ,0
Exp/Cntr=0.3,0.1

Type RM Length L Ch R = 1 ,3176.4  ,255.3,255.5,255.7
XS GIS Cut Line= 4
     1553775.861      338958.926      1553733.33      339418.258
     1553546.195      339677.695     1553503.665      339992.422
#Sta/Elev= 30
      10  851.86   110.3  804.01   140.4   789.2   150.4     785   180.5  775.18
   200.6   767.8   280.8  736.12     341  711.23   391.1  689.46   461.3  659.88
   491.3  646.52   501.3  642.74   511.3  640.13   588.7  628.82   601.2  628.02
   613.7  628.69   641.2  631.72   651.2  634.59   661.2  639.81   681.2  652.69
   691.2  657.01   721.2   664.5   741.2  671.49   771.2  683.82     811  701.46
   880.4  728.33  1019.4   791.1  1039.2  801.38  1059.1  812.64  1098.8  832.55
#Mann= 3 , 0 , 0
       0     .08       0   588.7    .045       0   613.7     .08       0
Bank Sta=588.7,613.7
XS Rating Curve= 0 ,0
Exp/Cntr=0.3,0.1

Type RM Length L Ch R = 1 ,2920.9  ,557.7,549.1,540.4
XS GIS Cut Line= 4
     1553329.289       338784.55     1553537.979       339265.94
     1553402.996       339451.86     1553286.758      339894.602
#Sta/Elev= 30
    10.1  881.15    70.6  857.26    90.8  847.32   141.3  820.29     222  783.82
   272.4   765.9   302.7  757.88     333  751.07   383.4  731.58   413.7  721.55
   433.9  713.82     454  704.09   504.5   676.9   554.6  655.94   584.6  646.06
   594.6  640.07  606.18  630.84  614.86  627.65   627.1  628.72   644.5  631.04
   744.4  634.27   754.4   635.8   814.1  657.11     844   662.7   853.9  666.04
   883.8  679.23   953.5  712.61  1062.9  751.41  1122.6  773.66  1212.2  816.24
#Mann= 3 , 0 , 0
    10.1     .08       0  606.18    .045       0   627.1     .08       0
#XS Ineff= 2 , 0
                          661.42          657.69
Permanent Ineff=
       F       F
Bank Sta=606.18,627.1
XS Rating Curve= 0 ,0
Exp/Cntr=0.3,0.1

Type RM Length L Ch R = 1 ,2371.8  ,160.5,159.3,158.7
XS GIS Cut Line= 4
     1553148.313      338700.542     1553028.611      339110.583
     1552924.191      339413.657      1552812.13      339732.012
#Sta/Elev= 30
     9.9  873.31   168.9  781.17   178.8  776.68   238.4  754.11   327.8  716.61
   377.5  692.74   497.3  633.13   507.3  628.65   517.3  625.82   534.9  622.48
   547.4  621.35   559.9  622.01   587.4  624.91   597.5  626.97   627.5  641.94
   637.5   646.1   647.5  648.61   677.6  651.86   707.6  652.75   717.7  654.24
   727.7  657.77   747.7  666.97   777.5  682.36   827.1   711.5     847  722.25
   896.6  743.24   956.2  767.21   985.9  780.89  1005.8   791.7  1085.2  841.48
#Mann= 3 , 0 , 0
       0     .08       0   534.9    .045       0   559.9     .08       0
Bank Sta=534.9,559.9
XS Rating Curve= 0 ,0
Exp/Cntr=0.3,0.1

Type RM Length L Ch R = 1 ,2212.5  ,431.4,438.3,444.7
XS GIS Cut Line= 3
     1553001.802      338635.693     1552842.397      339172.436
     1552674.316       339698.96
#Sta/Elev= 30
      10  891.39      40  874.15     150  797.57     170  784.74     180  779.58
     320  719.99   469.9   647.8   489.9  640.05   519.9  630.25   547.4  623.35
   559.9  620.85   572.4  621.14   620.2  624.09   650.4  629.12   680.5  632.37
   690.6  634.69   700.6  638.44   730.7   651.8   760.9  662.99     791  675.81
   831.2  694.43   871.4   714.7   891.5  723.96   921.7  735.08   961.9  751.04
  1022.2  770.26  1052.3  776.45  1082.5  783.91  1102.6  787.08  1112.6  787.64
#Mann= 3 , 0 , 0
       0     .08       0   547.4    .045       0   572.4     .08       0
Bank Sta=547.4,572.4
XS Rating Curve= 0 ,0
Exp/Cntr=0.3,0.1