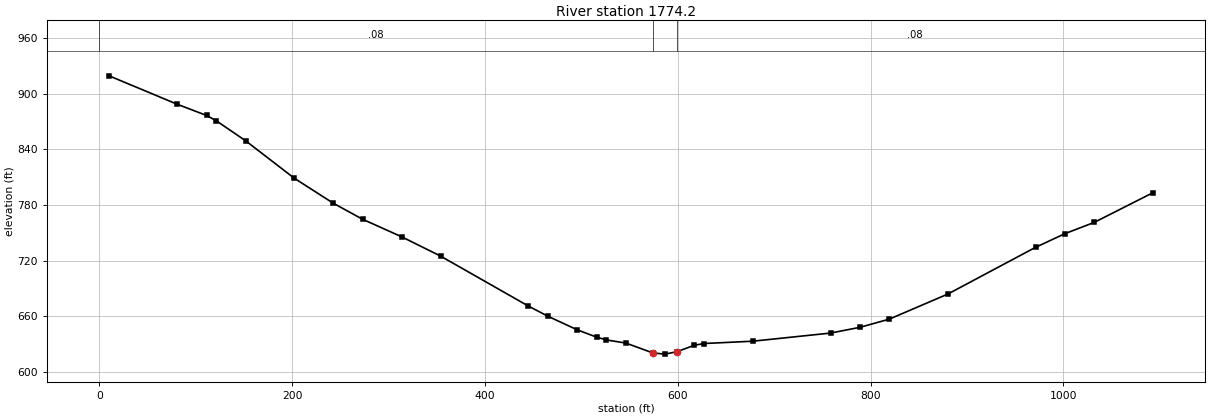
HEC-RAS study RFBULLCR.prj: RFBULLCR

--- RFBULLCR.g01 (geometry) --- (continued)

Type RM Length L Ch R = 1 ,1774.2  ,1813.8,1774.2,1734.4
XS GIS Cut Line= 3
     1552723.281      338517.526     1552450.552      338990.602
     1552168.385      339458.685
#Sta/Elev= 30
    10.1  919.13    80.9  888.47   111.2  876.45   121.3  870.73   151.7  849.19
   202.2  808.84   242.7   781.9     273  764.69   313.5  745.81   353.9  725.01
   444.9  671.24   465.2  660.22   495.5  645.67   515.7  637.73   525.8  634.71
   546.1  631.34     574  620.73   586.5  619.41     599  621.97   616.9  628.88
     627  630.83   677.6  633.32   758.6  642.11     789  648.31   819.3  657.07
   880.1  684.13   971.2  734.51  1001.5  749.14  1031.9  761.27  1092.6  793.16
#Mann= 3 , 0 , 0
       0     .08       0     574    .045       0     599     .08       0
Bank Sta=574,599
XS Rating Curve= 0 ,0
Exp/Cntr=0.3,0.1

Chan Stop Cuts=-1
Use User Specified Reach Order=0